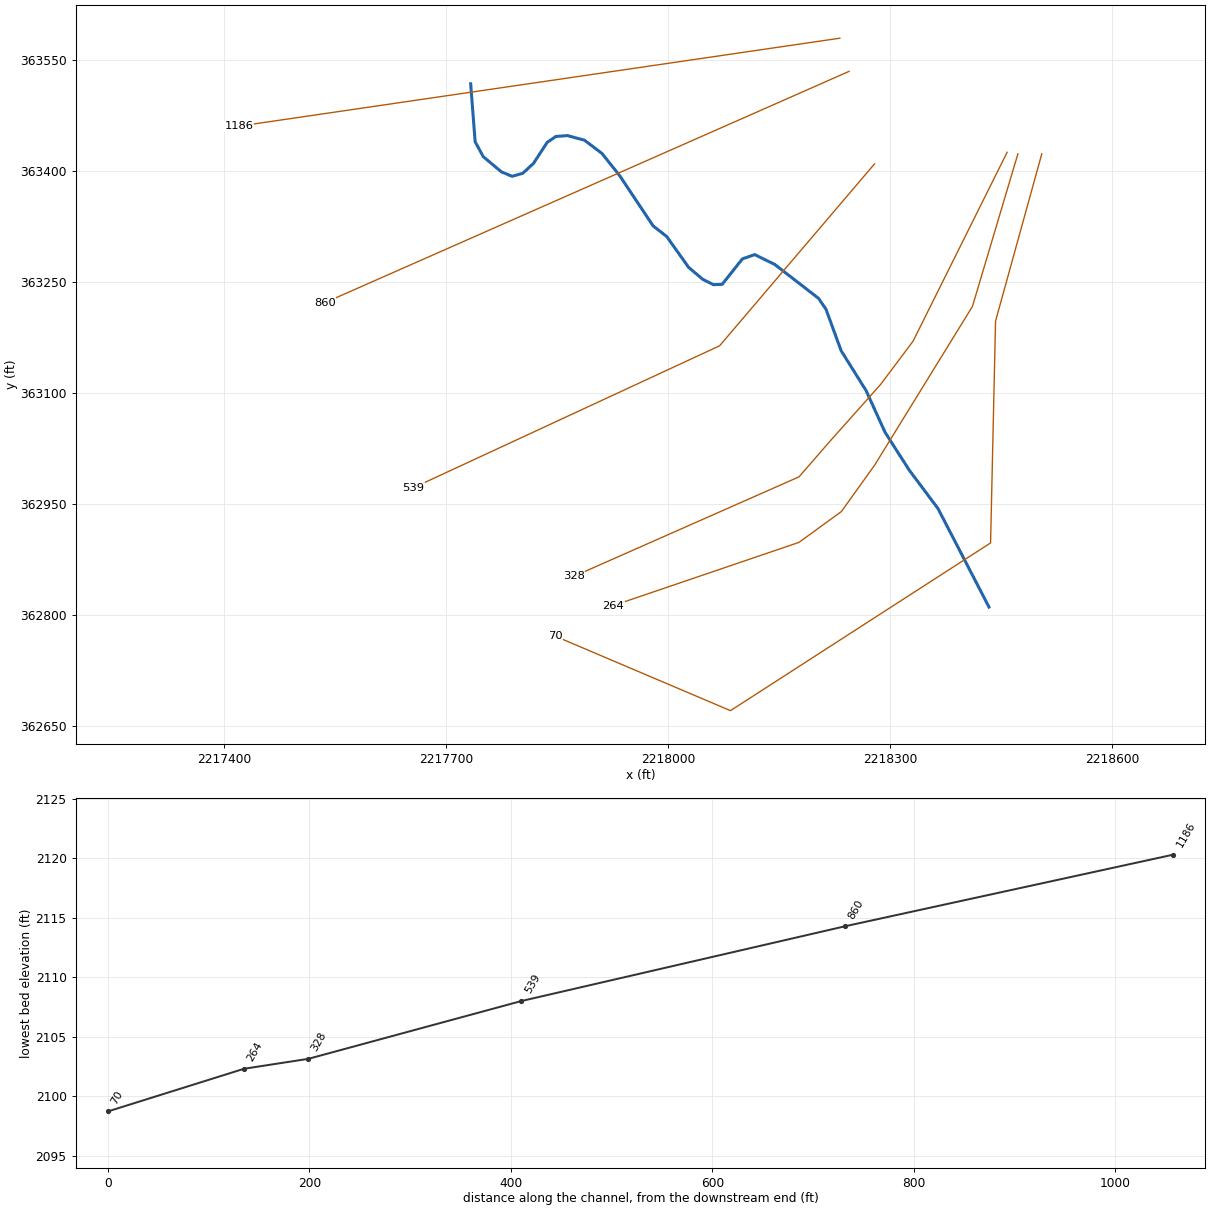
--- TWOMILERN.prj (project) ---

Proj Title=TWOMILERN
Current Plan=p01
Default Exp/Contr=0.3,0.1
English Units
Geom File=g01
Flow File=f01
Plan File=p01
Y Axis Title=Elevation
X Axis Title(PF)=Main Channel Distance
X Axis Title(XS)=Station
BEGIN DESCRIPTION:
Stream Name- Twomile Run
Flood Zone: Zone A
Greenbrier County, WV
County-Wide Study
WVDHSEM-2018-3, Flood Risk Project
HEC-RAS Version: 5.0.7
General Notes:
For the Hydrology Regression was used.
END DESCRIPTION:
DSS Export Rating Curves= 0
DSS Export Rating Curve Sorted= 0
DSS Export Volume Flow Curves= 0
DXF Filename=A2c.
DXF OffsetX= 0
DXF OffsetY= 0
DXF ScaleX= 1
DXF ScaleY= 10

--- TWOMILERN.p01 (plan) ---

Plan Title=Floodplain
Program Version=5.07
Short Identifier=Floodplain
Geom File=g01
Flow File=f01
Subcritical Flow
K Sum by GR= 0
Std Step Tol= 0.01
Critical Tol= 0.01
Num of Std Step Trials= 20
Max Error Tol= 0.3
Flow Tol Ratio= 0.001
Split Flow NTrial= 30
Split Flow Tol= 0.02
Split Flow Ratio= 0.02
Log Output Level= 0
Friction Slope Method= 1
Unsteady Friction Slope Method= 2
Unsteady Bridges Friction Slope Method= 1
Parabolic Critical Depth
Global Vel Dist= 0 , 0 , 0
Global Log Level= 0
CheckData=True
Encroach Param=-1 ,0,0, 0
Computation Interval=1MIN
Output Interval=1HOUR
Instantaneous Interval=1HOUR
Mapping Interval=1HOUR
Computation Time Step Use Courant=        0
Computation Time Step Use Time Series=    0
Computation Time Step Count To Double=0
Computation Time Step Max Doubling=0
Computation Time Step Max Halving=0
Computation Time Step Residence Courant=0
Run HTab= 0
Run UNet= 0
Run Sediment= 0
Run PostProcess= 0
Run WQNet= 0
Run RASMapper= 0
UNET Theta= 1
UNET Theta Warmup= 1
UNET ZTol= 0.02
UNET ZSATol= 0.02
UNET MxIter= 20
UNET Max Iter WO Improvement= 0
UNET MaxInSteps= 0
UNET DtIC= 0
UNET DtMin= 0
UNET MaxCRTS= 20
UNET WFStab= 2
UNET SFStab= 1
UNET WFX= 1
UNET SFX= 1
UNET 1D Methodology=Finite Difference
UNET DSS MLevel= 4
UNET Pardiso=0
UNET DZMax Abort= 100
UNET Use Existing IB Tables=-1
UNET Froude Reduction=False
UNET Froude Limit= 0.8
UNET Froude Power= 4
UNET D1 Cores= 0
UNET D2 Coriolis=0
UNET D2 Cores= 0
UNET D2 Theta= 1
UNET D2 Theta Warmup= 1
UNET D2 Z Tol= 0.01
UNET D2 Volume Tol= 0.01
UNET D2 Max Iterations= 20
UNET D2 Equation= 0
UNET D2 RampUpFraction=0.1
UNET D2 TimeSlices= 1
UNET D2 BCVolumeCheck=0
UNET D1D2 MaxIter= 0
UNET D1D2 ZTol=0.01
UNET D1D2 QTol=0.1
UNET D1D2 MinQTol=1
Write IC File= 0
Write IC File at Fixed DateTime=0
Write IC File at Sim End=0
Echo Input=False
Echo Parameters=False
Echo Output=False
Write Detailed= 0
HDF Write Warmup=0
HDF Write Time Slices=0
HDF Flush=0
HDF Face Node Velocities=0
HDF Compression= 1
HDF Chunk Size= 1
HDF Spatial Parts= 1
HDF Use Max Rows=0
HDF Fixed Rows= 1
Calibration Method= 0
Calibration Iterations= 20
Calibration Max Change=0.05
Calibration Tolerance=0.2
Calibration Maximum=1.5
Calibration Minimum=0.5
Calibration Optimization Method= 1
WQ AD Non Conservative
WQ ULTIMATE=-1
WQ Max Comp Step=1HOUR
WQ Output Interval=15MIN
WQ Output Selected Increments= 0
WQ Output face flow=0
WQ Output face velocity=0
WQ Output face area=0
WQ Output face dispersion=0
WQ Output cell volume=0
WQ Output cell surface area=0
WQ Output cell continuity=0
WQ Output cumulative cell continuity=0
WQ Output face conc=0
WQ Output face dconc_dx=0
WQ Output face courant=0
WQ Output face peclet=0
WQ Output face adv mass=0
WQ Output face disp mass=0
WQ Output cell mass=0
WQ Output cell source sink temp=0
WQ Output nsm pathways=0
WQ Output nsm derived pathways=0
WQ Output MaxMinRange=-1
WQ Daily Max Min Mean=-1
WQ Daily Range=0
WQ Daily Time=0
WQ Create Restart=0
WQ Fixed Restart=0
WQ System Summary=0
WQ Write To DSS=0
WQ Use Fixed Temperature=0
Sorting and Armoring Iterations= 10
XS Update Threshold= 0.02
Bed Roughness Predictor= 0
Hydraulics Update Threshold= 0.02
Energy Slope Method= 1
Volume Change Method= 1
Sediment Retention Method= 0
XS Weighting Method= 0
Number of US Weighted Cross Sections= 1
Number of DS Weighted Cross Sections= 1
Upstream XS Weight=0
Main XS Weight=1
Downstream XS Weight=0
Number of DS XS's Weighted with US Boundary= 1
Upstream Boundary Weight= 1
Weight of XSs Associated with US Boundary= 0
Number of US XS's Weighted with DS Boundary= 1
Downstream Boundary Weight= 0.5
Weight of XSs Associated with DS Boundary= 0.5
Percentile Method= 0
Sediment Output Level= 3
Mass or Volume Output= 0
Output Increment Type= 1
Profile and TS Output Increment= 1
XS Output Flag= 0
XS Output Increment= 10
Write Gradation File= 0
Read Gradation Hotstart= 0
Write HDF5 File= 1
Write Binary Output= 1
Write DSS Sediment File= 0
SV Curve= 0
Specific Gage Flag= 0

--- TWOMILERN.f01 (steady flow) ---

Flow Title=Flow
Program Version=5.07
Number of Profiles= 6
Profile Names=f1p,f10p,f4p,f2p,f02p,f1pplus
River Rch & RM=LAURELRN2,Main            ,16185
     488     256     342     413     684     722
River Rch & RM=LAURELRN2,Main            ,15475
     566     299     398     479     791     838
River Rch & RM=LAURELRN2,Main            ,13512
     655     348     462     555     913     969
River Rch & RM=LAURELRN2,Main            ,11607
     732     390     517     621    1020    1080
River Rch & RM=LAURELRN2,Main            ,8528
     852     457     604     724    1180    1260
River Rch & RM=LAURELRN2,Main            ,6084
     949     511     674     807    1310    1400
River Rch & RM=LAURELRN2,Main            ,2993
    1060     571     751     899    1460    1560
River Rch & RM=MEADOWCK1,Main            ,75581
     529     279     371     448     740     782
River Rch & RM=MEADOWCK1,Main            ,73978
     598     316     420     506     834     884
River Rch & RM=MEADOWCK1,Main            ,71430
     678     361     478     575     945    1000
River Rch & RM=MEADOWCK1,Main            ,69203
     792     424     560     672    1100    1170
River Rch & RM=MEADOWCK1,Main            ,67339
     882     474     625     749    1220    1300
River Rch & RM=MEADOWCK1,Main            ,64109
    1010     548     721     863    1400    1500
River Rch & RM=MEADOWCK1,Main            ,61239
    1140     619     812     971    1570    1690
River Rch & RM=MEADOWCK1,Main            ,59576
    1280     700     917    1090    1770    1900
River Rch & RM=MEADOWCK1,Main            ,56054
    1450     794    1040    1240    1990    2140
River Rch & RM=MEADOWCK1,Main            ,50980
    1720     950    1240    1470    2360    2550
River Rch & RM=MEADOWCK1,Main            ,44209
    1940    1080    1400    1660    2650    2870
River Rch & RM=MEADOWCK1,Main            ,42625
    1840    1020    1320    1570    2510    2720
River Rch & RM=MEADOWCK1,Main            ,38864
    2190    1220    1580    1870    2980    3230
River Rch & RM=MEADOWCK1,Main            ,31946
    2500    1400    1810    2140    3390    3690
River Rch & RM=MEADOWCK1,Main            ,24140
    2780    1560    2020    2390    3780    4120
River Rch & RM=MEADOWCK1,Main            ,14473
    3730    2120    2720    3210    5030    5510
River Rch & RM=MFANTNYCK,Main            ,62239
    1310     714     935    1120    1800    1940
River Rch & RM=MFANTNYCK,Main            ,61636
    1410     772    1010    1200    1940    2090
River Rch & RM=MFANTNYCK,Main            ,58106
    1580     868    1130    1350    2160    2330
River Rch & RM=MFANTNYCK,Main            ,55360
    1820    1010    1310    1560    2490    2690
River Rch & RM=MFANTNYCK,Main            ,52938
    2030    1120    1460    1730    2760    3000
River Rch & RM=MFANTNYCK,Main            ,48015
    2310    1290    1670    1980    3150    3420
River Rch & RM=MFANTNYCK,Main            ,44550
    2730    1530    1980    2340    3700    4030
River Rch & RM=MFANTNYCK,Main            ,38407
    3100    1750    2250    2660    4200    4590
River Rch & RM=MFANTNYCK,Main            ,29623
    3460    1960    2520    2980    4680    5120
River Rch & RM=MFANTNYCK,Main            ,25319
    3880    2210    2840    3340    5230    5740
River Rch & RM=MFANTNYCK,Main            ,16951
    4320    2470    3160    3720    5810    6390
River Rch & RM=MFANTNYCK,Main            ,12276
    4850    2780    3560    4180    6510    7170
River Rch & RM=NFANTNYCK,Main            ,44991
    1410     771    1010    1200    1940    2080
River Rch & RM=NFANTNYCK,Main            ,42260
    1650     907    1180    1410    2260    2440
River Rch & RM=NFANTNYCK,Main            ,38018
    1880    1040    1360    1610    2570    2790
River Rch & RM=NFANTNYCK,Main            ,34796
    2230    1240    1610    1910    3040    3300
River Rch & RM=NFANTNYCK,Main            ,29090
    2490    1390    1800    2140    3390    3680
River Rch & RM=NFANTNYCK,Main            ,20166
    2840    1590    2060    2430    3840    4190
River Rch & RM=NFANTNYCK,Main            ,11738
    3200    1810    2330    2750    4330    4740
River Rch & RM=NFANTNYCK,Main            ,8976
    3560    2020    2600    3060    4810    5270
River Rch & RM=TWOMILERN,Main            ,1186
     601     318     423     509     838     889
Boundary for River Rch & Prof#=LAURELRN2,Main            , 1
Up Type= 0
Dn Type= 3
Dn Slope=0.035124
Boundary for River Rch & Prof#=LAURELRN2,Main            , 2
Up Type= 0
Dn Type= 3
Dn Slope=0.035124
Boundary for River Rch & Prof#=LAURELRN2,Main            , 3
Up Type= 0
Dn Type= 3
Dn Slope=0.035124
Boundary for River Rch & Prof#=LAURELRN2,Main            , 4
Up Type= 0
Dn Type= 3
Dn Slope=0.035124
Boundary for River Rch & Prof#=LAURELRN2,Main            , 5
Up Type= 0
Dn Type= 3
Dn Slope=0.035124
Boundary for River Rch & Prof#=LAURELRN2,Main            , 6
Up Type= 0
Dn Type= 3
Dn Slope=0.035124
Boundary for River Rch & Prof#=MEADOWCK1,Main            , 1
Up Type= 0
Dn Type= 3
Dn Slope=0.011297
Boundary for River Rch & Prof#=MEADOWCK1,Main            , 2
Up Type= 0
Dn Type= 3
Dn Slope=0.011297
Boundary for River Rch & Prof#=MEADOWCK1,Main            , 3
Up Type= 0
Dn Type= 3
Dn Slope=0.011297
Boundary for River Rch & Prof#=MEADOWCK1,Main            , 4
Up Type= 0
Dn Type= 3
Dn Slope=0.011297
Boundary for River Rch & Prof#=MEADOWCK1,Main            , 5
Up Type= 0
Dn Type= 3
Dn Slope=0.011297
Boundary for River Rch & Prof#=MEADOWCK1,Main            , 6
Up Type= 0
Dn Type= 3
Dn Slope=0.011297
Boundary for River Rch & Prof#=MFANTNYCK,Main            , 1
Up Type= 0
Dn Type= 3
Dn Slope=0.001473
Boundary for River Rch & Prof#=MFANTNYCK,Main            , 2
Up Type= 0
Dn Type= 3
Dn Slope=0.001473
Boundary for River Rch & Prof#=MFANTNYCK,Main            , 3
Up Type= 0
Dn Type= 3
Dn Slope=0.001473
Boundary for River Rch & Prof#=MFANTNYCK,Main            , 4
Up Type= 0
Dn Type= 3
Dn Slope=0.001473
Boundary for River Rch & Prof#=MFANTNYCK,Main            , 5
Up Type= 0
Dn Type= 3
Dn Slope=0.001473
Boundary for River Rch & Prof#=MFANTNYCK,Main            , 6
Up Type= 0
Dn Type= 3
Dn Slope=0.001473
Boundary for River Rch & Prof#=NFANTNYCK,Main            , 1
Up Type= 0
Dn Type= 3
Dn Slope=0.006644
Boundary for River Rch & Prof#=NFANTNYCK,Main            , 2
Up Type= 0
Dn Type= 3
Dn Slope=0.006644
Boundary for River Rch & Prof#=NFANTNYCK,Main            , 3
Up Type= 0
Dn Type= 3
Dn Slope=0.006644
Boundary for River Rch & Prof#=NFANTNYCK,Main            , 4
Up Type= 0
Dn Type= 3
Dn Slope=0.006644
Boundary for River Rch & Prof#=NFANTNYCK,Main            , 5
Up Type= 0
Dn Type= 3
Dn Slope=0.006644
Boundary for River Rch & Prof#=NFANTNYCK,Main            , 6
Up Type= 0
Dn Type= 3
Dn Slope=0.006644
Boundary for River Rch & Prof#=TWOMILERN,Main            , 1
Up Type= 0
Dn Type= 3
Dn Slope=0.021324
Boundary for River Rch & Prof#=TWOMILERN,Main            , 2
Up Type= 0
Dn Type= 3
Dn Slope=0.021324
Boundary for River Rch & Prof#=TWOMILERN,Main            , 3
Up Type= 0
Dn Type= 3
Dn Slope=0.021324
Boundary for River Rch & Prof#=TWOMILERN,Main            , 4
Up Type= 0
Dn Type= 3
Dn Slope=0.021324
Boundary for River Rch & Prof#=TWOMILERN,Main            , 5
Up Type= 0
Dn Type= 3
Dn Slope=0.021324
Boundary for River Rch & Prof#=TWOMILERN,Main            , 6
Up Type= 0
Dn Type= 3
Dn Slope=0.021324
DSS Import GetInterval= 0
DSS Import GetPeak= 0
DSS Import FillOption= 0

--- TWOMILERN.g01 (geometry) ---

Geom Title=Geometry
Program Version=5.07

River Reach=TWOMILERN       ,Main
Reach XY= 30
2217733.02310605363518.0207299742217739.09986556363439.636372313
2217750.14052589 363419.470730232217774.80681513 363398.86873731
2217789.15750822 363393.045258152217803.52329314363397.151221067
2217817.92615147363410.4904332312217836.49665239363438.926071897
2217848.03928022363446.8236938862217863.90604639363448.055646807
2217886.74819231363441.8624177282217910.36855188363424.061272234
 2217934.8051828 363393.369404482217979.56920089363326.094604641
2217998.07703789363311.551326647 2218027.5195643 363270.06617339
2218046.78002447363253.7601036432218061.11529763363246.602965727
2218072.92728189363247.1219935572218100.20741105363281.419825226
2218116.99281055 363287.246585222218144.03967246 363273.90901348
2218203.21278247363228.0770841392218213.31774914363213.175211057
2218233.65990005363157.4673172242218267.43739155 363103.41296339
2218293.18865238 363046.835648732218325.74600197362995.995855391
2218364.58844396362944.0894631452218433.48102272362811.001146644

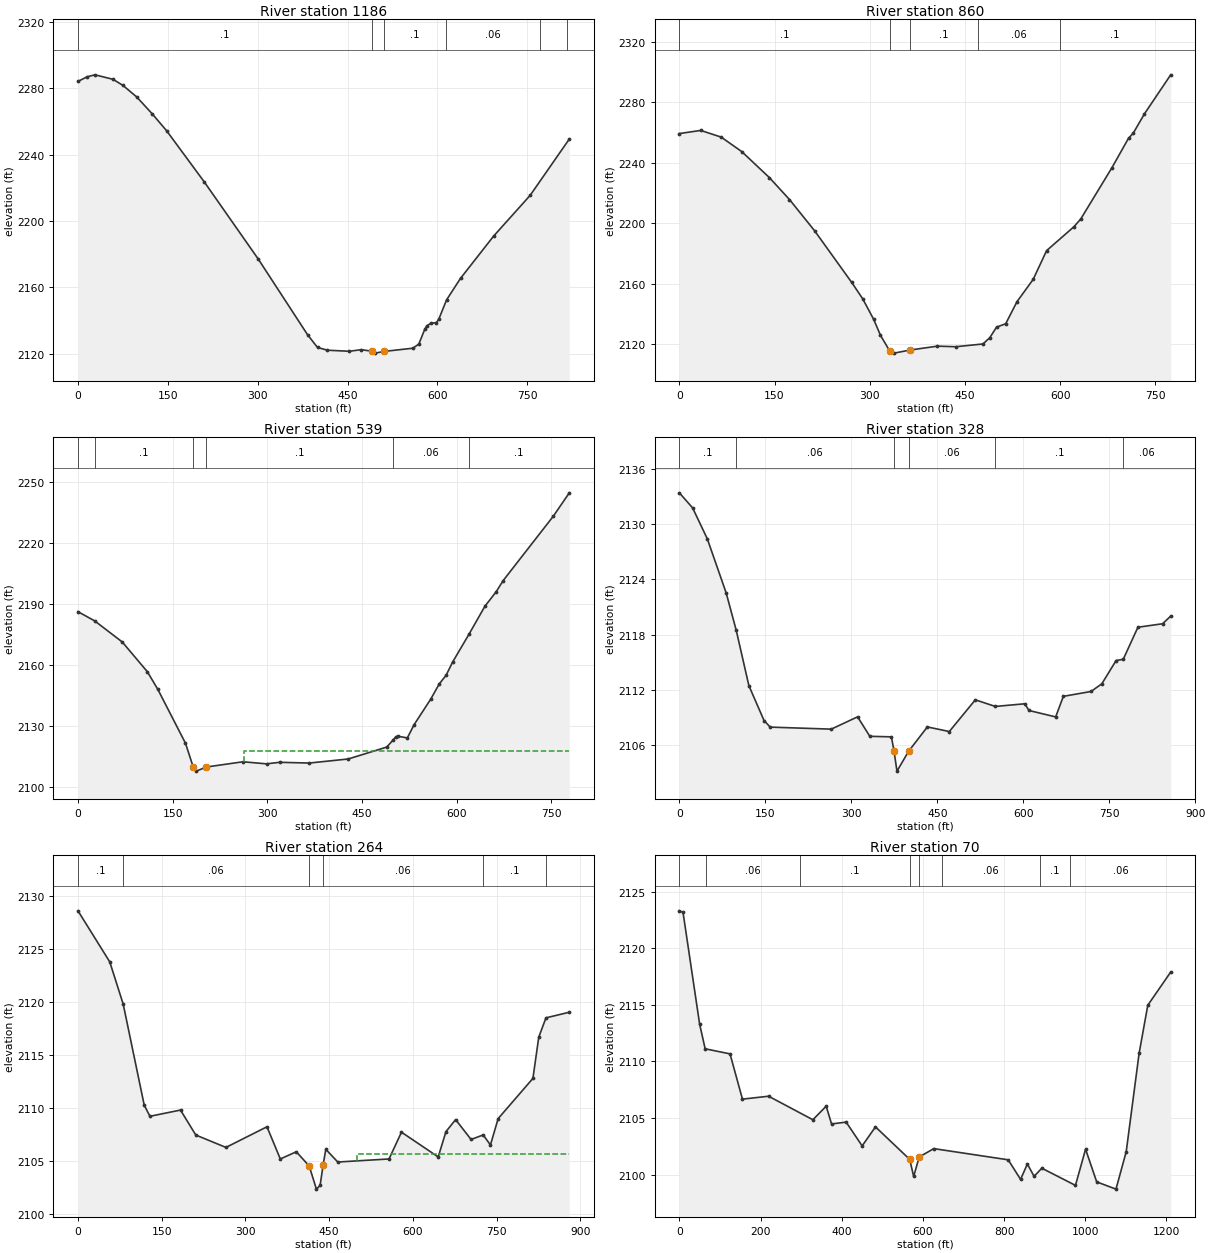
Type RM Length L Ch R = 1 ,1186    ,321.5,326.3,314.2
XS GIS Cut Line= 2
2218231.96141264363579.647247151 2217420.5030618363460.897156566
#Sta/Elev= 30
       0 2284.07    15.2 2286.87    28.4 2288.05    58.3 2285.37    74.9 2281.72
    98.1 2274.69     124  2264.5   147.8 2254.41   210.8 2223.51     301 2176.96
   383.2  2131.4   399.8 2123.73   416.4 2122.07   452.9 2121.43   472.8 2122.38
   491.22121.438     496 2120.31  511.312121.356     559 2123.27   568.9 2125.76
   578.9 2134.74   582.2 2136.71   588.8 2138.29   598.3 2138.72   602.1 2140.64
   615.3 2152.45   638.5 2165.38   693.8 2190.86   754.7 2215.38   820.1 2249.35
#Mann= 6 ,-1 , 0
       0      .1       0   491.2    .045       0  511.31      .1       0
   614.3     .06       0  771.97     .12       0  816.27      .1       0
Bank Sta=491.2,511.31
XS Rating Curve= 0 ,0
Exp/Cntr=0.3,0.1

Type RM Length L Ch R = 1 ,860     ,313.5,321,326.1
XS GIS Cut Line= 2
2218244.46138763363534.8556700652217536.12783055363222.355638891
#Sta/Elev= 30
       0  2259.3    33.7 2261.37    65.9 2256.95    98.2 2247.42   141.9 2230.19
   173.5 2215.74     213 2195.15   271.3 2161.13   288.7 2150.29   305.9  2136.8
   316.9 2126.07  331.232115.818   338.4 2114.28   363.3 2116.31   406.6 2118.89
   435.5 2118.51   478.3 2120.32   489.1 2124.45   499.8 2131.44   514.2 2133.69
   532.1 2148.32   557.4 2162.92   578.7 2181.99   621.8 2197.78   632.5  2202.9
   681.8 2236.88   707.8 2256.25     715 2259.44   732.9 2272.36   774.2 2298.09
#Mann= 5 ,-1 , 0
       0      .1       0  331.23    .045       0   363.3      .1       0
  470.85     .06       0  599.23      .1       0
Bank Sta=331.23,363.3
XS Rating Curve= 0 ,0
Exp/Cntr=0.3,0.1

Type RM Length L Ch R = 1 ,539     ,211.5,211.5,211.9
XS GIS Cut Line= 3
2218278.83631888363409.8555919832218069.46140955363164.022094145
2217655.91958572362972.355482727
#Sta/Elev= 30
       0 2186.38    26.5 2181.85    70.2 2171.48     110 2156.85   126.6 2148.16
   170.4 2121.71   182.5 2110.15   187.6    2108   203.4 2110.02   261.6  2112.6
   298.8 2111.58   319.8 2112.34   366.5 2111.97   428.3 2113.97   489.4 2119.83
   499.2 2123.23   503.9 2124.92   507.5 2125.12     522 2124.33   532.8 2130.87
   559.2 2143.46   572.6 2150.89   583.4 2155.09   593.8 2161.64   619.6 2175.24
   644.9 2189.03   662.9 2196.22   673.8 2201.64   753.4 2233.34   778.7 2244.81
#Mann= 6 ,-1 , 0
       0      .1       0    26.5      .1       0   182.5    .045       0
   203.4      .1       0   499.2     .06       0   619.6      .1       0
#XS Ineff= 2 , 0
                          262.94         2118.03
Permanent Ineff=
       F       F
Bank Sta=182.5,203.4
XS Rating Curve= 0 ,0
Exp/Cntr=0.5,0.3

Type RM Length L Ch R = 1 ,328     ,59.1,63.6,63.5
XS GIS Cut Line= 6
 2218458.0029553 363425.480560722218330.91954805363170.272081643
2218287.16963555363111.9388649762218218.41977306363034.855685815
2218176.75286163362986.9387868942217872.58647522362852.563727558
#Sta/Elev= 30
       0 2133.43    23.1 2131.79    48.7 2128.43    81.7 2122.53    99.2 2118.47
   121.3 2112.44   147.7 2108.65   158.5 2107.93     265 2107.71     311 2109.05
   332.3 2106.93     370 2106.87   374.4 2105.37   379.7 2103.14   400.1 2105.31
   432.7 2107.95     471 2107.45   516.4  2110.9   551.3 2110.18   602.8 2110.47
     610 2109.74   656.6 2109.04     670 2111.28   718.4 2111.81   737.2 2112.65
   762.1 2115.18   774.5 2115.31   800.1  2118.8   843.1 2119.18   857.3 2120.01
#Mann= 6 ,-1 , 0
       0      .1       0    99.2     .06       0   374.4    .045       0
   400.1     .06       0   551.3      .1       0   774.5     .06       0
#XS Ineff= 2 , 0
           361.4  2105.6   487.1          2105.6
Permanent Ineff=
       F       F
Bank Sta=374.4,400.1
XS Rating Curve= 0 ,0
Exp/Cntr=0.5,0.3

Type RM Length L Ch R = 1 ,264     ,139.6,135.3,131.1
XS GIS Cut Line= 6
2218472.58625947363423.3972315642218411.12804906363217.147315979
2218278.83631888363002.5637556462218234.04474181362940.063880637
2218176.75286163362898.3972973082217925.71136898362812.980473399
#Sta/Elev= 30
       0  2128.6    56.9 2123.78      81 2119.79   118.7 2110.24   128.9 2109.19
   183.7 2109.78   211.1 2107.42   265.1 2106.25   338.6  2108.2   362.5 2105.16
   391.2 2105.84   414.3 2104.49   427.2 2102.31   433.8 2102.66   439.2 2104.58
     444 2106.07   465.5 2104.87   557.3 2105.16   579.6 2107.69   645.4 2105.35
   659.3 2107.74   676.6 2108.88   704.3    2107     726 2107.43     739 2106.48
   752.8 2108.97   815.1 2112.77   825.6 2116.67   838.5 2118.49   880.3 2119.02
#Mann= 6 ,-1 , 0
       0      .1       0      81     .06       0   414.3    .045       0
   439.2     .06       0     726      .1       0   838.5     .06       0
#XS Ineff= 2 , 0
             354  2105.6   499.2          2105.6
Permanent Ineff=
       F       F
Bank Sta=414.3,439.2
XS Rating Curve= 0 ,0
Exp/Cntr=0.5,0.3

Type RM Length L Ch R = 1 ,70      ,143.38,128.83,143.34
XS GIS Cut Line= 5
2218504.87786156363423.3972315642218442.37798655  363197.3556889
2218435.65295459 362897.647787022218084.15378371 362671.02121944
2217846.78212177362771.862038381
#Sta/Elev= 30
       0 2123.31       9 2123.18    49.9  2113.3    63.5 2111.12   124.8 2110.67
   155.4 2106.67   219.8 2106.93   328.9 2104.85   361.7 2106.05   374.9 2104.48
   410.9 2104.64   450.3 2102.54   483.1 2104.22   567.4 2101.35   577.2 2099.84
   590.82101.556   626.7  2102.3   810.1 2101.31   840.6 2099.58   857.3 2100.94
   873.9 2099.85   892.9 2100.57   975.8 2099.05  1000.7 2102.25  1028.1 2099.36
  1075.6 2098.72  1100.8 2102.02  1132.6 2110.72    1154 2114.97  1210.4  2117.9
#Mann= 8 ,-1 , 0
       0      .1       0   65.53     .06       0  298.25      .1       0
   567.4    .045       0   590.8     .12       0  646.96     .06       0
  888.18      .1       0  963.49     .06       0
Bank Sta=567.4,590.8
XS Rating Curve= 0 ,0
Exp/Cntr=0.3,0.1
LCMann Table=0

Chan Stop Cuts=-1
Use User Specified Reach Order=0
Composite Channel Slope=5